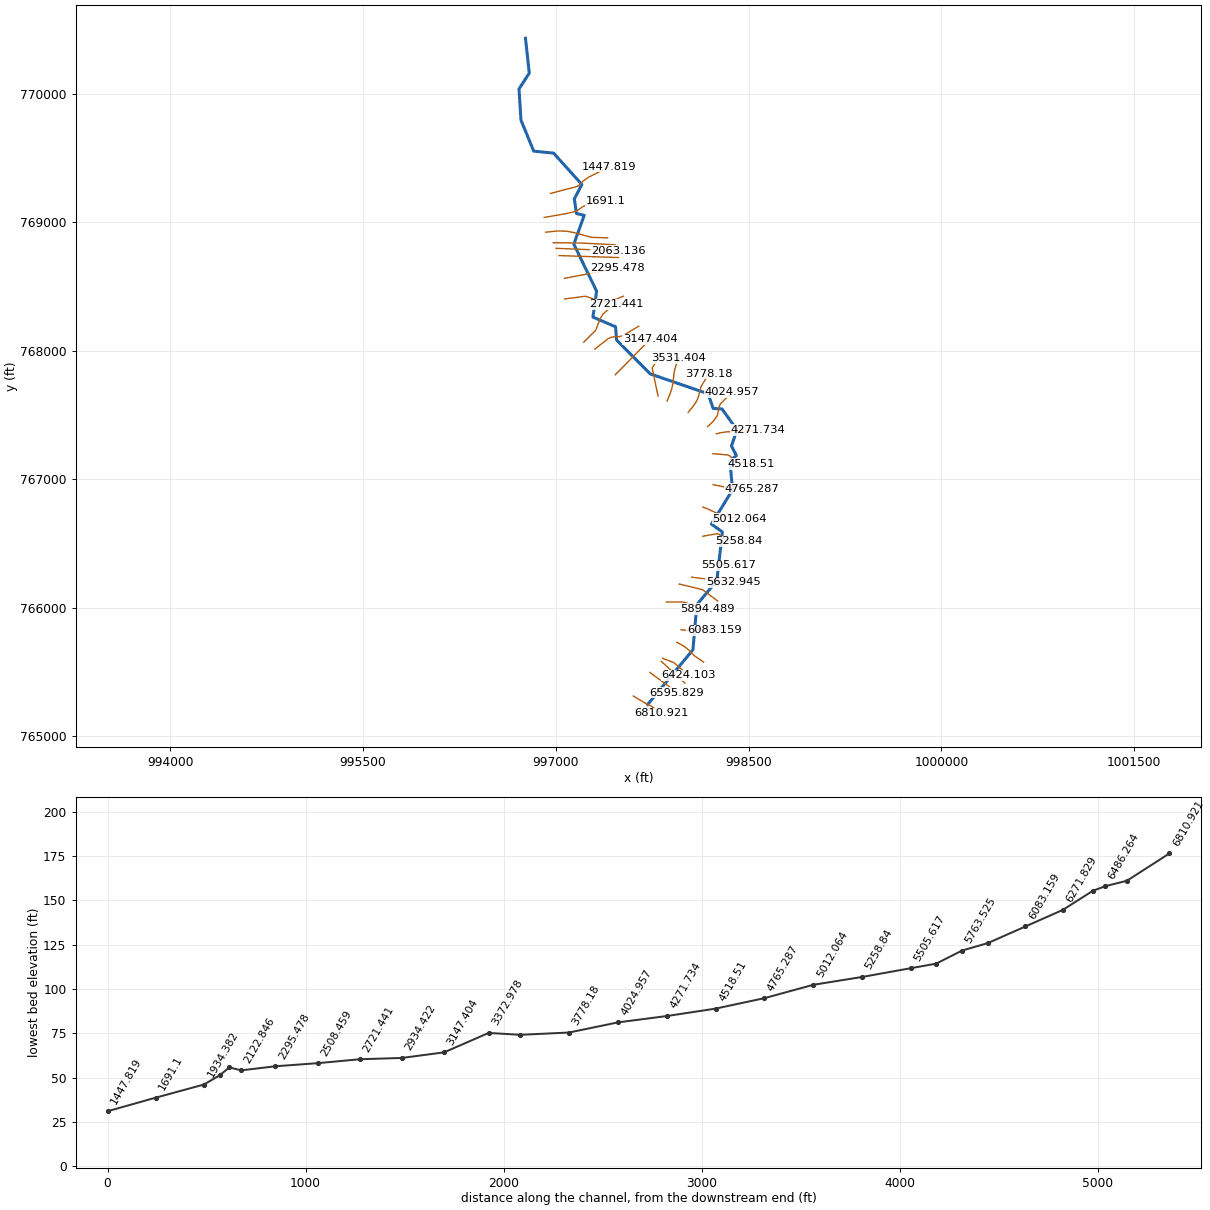
--- 157_ras.prj (project) ---

Proj Title=157
Current Plan=p01
Default Exp/Contr=0.3,0.1
English Units
Geom File=g01
Flow File=f01
Plan File=p01
Y Axis Title=Elevation
X Axis Title(PF)=Main Channel Distance
X Axis Title(XS)=Station
BEGIN DESCRIPTION:
RFD model 157 exported to HEC-RAS
END DESCRIPTION:

--- 157_ras.p01 (plan) ---

Plan Title=Plan 01
Program Version=4.10
Short Identifier=Plan 01
Geom File=g01
Flow File=f01
Subcritical Flow
Calc Critical at every XS
Secant Critical Depth

--- 157_ras.f01 (steady flow) ---

Flow Title=Flow 01
Program Version=5.01
Number of Profiles= 6
Profile Names=10yr,25yr,50yr,100yr,100plus,500yr
River Rch & RM=157,38,6810.921
   82.13  156.87  237.58  326.93  477.31 1103.73
River Rch & RM=157,38,5632.945
   84.82  162.02  245.42  337.74   493.1 1135.16
River Rch & RM=157,38,5505.617
   85.43  163.21  247.22  340.22  496.73 1142.36
River Rch & RM=157,38, 5258.84
   94.77  181.15  274.52  377.89  551.71  1250.7
River Rch & RM=157,38,5012.064
   97.35  186.12   282.1  388.36     567 1280.65
River Rch & RM=157,38,4765.287
   99.51  190.28  288.45  397.14  579.83 1305.78
River Rch & RM=157,38, 4518.51
  104.76  200.41  303.92  418.55  611.08 1366.66
River Rch & RM=157,38,4271.734
  107.26  205.25  311.31  428.77  626.01  1395.6
River Rch & RM=157,38,4024.957
  111.67  213.75  324.29  446.74  652.24 1446.23
River Rch & RM=157,38, 3778.18
  114.14  218.53  331.58  456.83  666.98 1474.54
River Rch & RM=157,38,3531.404
  116.03  222.19  337.17  464.57  678.27 1496.18
River Rch & RM=157,38,3372.978
  124.26   238.1   361.5  498.26  727.46 1589.95
River Rch & RM=157,38,3147.404
  131.25  251.63   382.2  526.94  769.33 1669.22
River Rch & RM=157,38,2934.422
   133.4  255.81  388.62  535.86  782.36 1693.95
River Rch & RM=157,38,2721.441
  136.45  261.74  397.71  548.48  800.79 1728.73
River Rch & RM=157,38,2508.459
  166.12   319.2  485.63  670.33  978.68 2057.28
River Rch & RM=157,38,2295.478
  166.79  320.51  487.66  673.15   982.8 2064.89
River Rch & RM=157,38,2122.846
  170.31   327.4  498.26  687.93 1004.38 2104.65
River Rch & RM=157,38,2014.385
  171.48  329.69  501.79  692.84 1011.55 2117.84
River Rch & RM=157,38,  1691.1
  175.31  337.18  513.34  708.93 1035.04 2160.96
River Rch & RM=157,38,1447.819
  179.29  344.96  525.32  725.63 1059.42 2205.59
River Rch & RM=157,38,1204.537
  180.94  348.19   530.3  732.57 1069.56 2224.08
River Rch & RM=157,38,961.2553
  184.21   354.6  540.18  746.36 1089.69 2260.88
River Rch & RM=157,38,717.9737
  187.29  360.64  549.51  759.39 1108.71 2295.63
River Rch & RM=157,38,474.6921
  188.88  363.78  554.37  766.19 1118.64 2313.83
River Rch & RM=157,38,231.4105
  193.32  372.53  567.92  785.16 1146.34 2364.51
River Rch & RM=157,38, 77.7765
  193.79  373.47  569.37  787.19  1149.3 2369.91
River Rch & RM=157,38, 32.0936
  195.06  375.96  573.22  792.59 1157.18  2384.3
Boundary for River Rch & Prof#=157,38,1
Up Type= 0
Dn Type= 2
Boundary for River Rch & Prof#=157,38,2
Up Type= 0
Dn Type= 2
Boundary for River Rch & Prof#=157,38,2
Up Type= 0
Dn Type= 2
Boundary for River Rch & Prof#=157,38,2
Up Type= 0
Dn Type= 2
Boundary for River Rch & Prof#=157,38,2
Up Type= 0
Dn Type= 2
Boundary for River Rch & Prof#=157,38,2
Up Type= 0
Dn Type= 2

--- 157_ras.g01 (geometry) ---

Geom Title=157
Program Version=4.10

River Reach=157,38
Reach XY= 30
997714.306405489765248.185930943998066.437909099765673.915679898
 998096.68053143766024.374303173998252.341087465 766211.16697044
998295.410274122766590.007346985998210.351874607766651.074782726
998374.125406148766917.302272654998354.103638531767145.119772877
998404.485336648767184.136589932998365.986184837767259.272809248
998409.266864271767384.723774973998292.368087578767547.179285694
998223.877442897767551.626730151998183.850442801767665.481308284
997733.769063578767820.252375445997472.633735212768082.743028112
997464.253929467768186.721798773997288.135128916 768262.32835458
997316.890580403768463.370185187997139.523896635 768829.53097098
997220.533973161769053.973468107997160.448408755769067.315801477
997143.518054516769180.794936357997201.854706408769294.135468861
996982.150950164769537.855425161996827.439169438769553.363450939
996728.388964534769794.693996153996712.937491656770036.788031336
996792.926596629770161.152650915996763.294126409770431.061002722

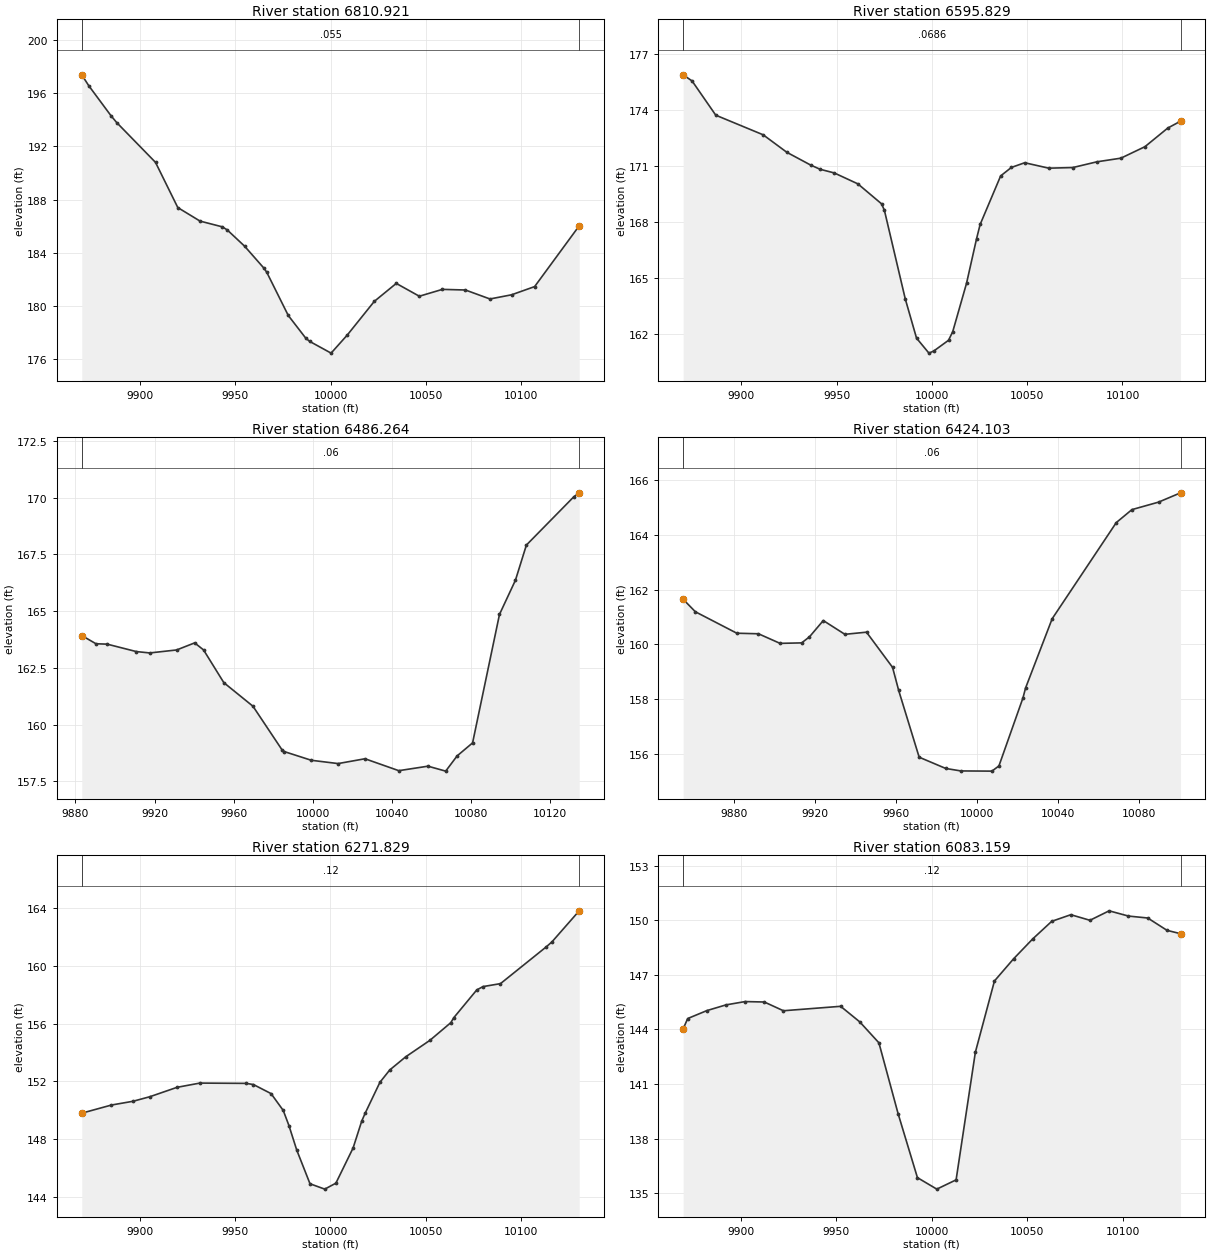
Type RM Length L Ch R = 1 ,6810.921,215.091400,215.091400,215.091400
XS GIS Cut Line= 6
997601.902941603765314.464157492997684.038089306765264.834680411
997713.802338609765249.507262309997715.627736856765248.689997823
997742.466191632765234.357773392 997824.33065846765178.682176326
#Sta/Elev= 26
9869.556197.38069873.175196.56969884.858194.30869887.856193.79229908.226190.7964
 9919.91187.39719931.594186.37869943.277185.94729945.865185.71339954.961184.4909
9965.201 182.8199966.603  182.529977.851179.28029987.002177.57969989.099  177.33
10000.31176.449910008.83177.816610022.96180.341810034.49181.693610046.58180.7287
10058.68 181.24510070.77 181.19710083.63180.523210094.96180.836710107.05181.4531
10130.43186.0241
#Mann= 3 , 0 , 0
9869.556   0.055       09869.556   0.055       010130.43   0.055       0
#XS Ineff= 2 , 0
       0                               0
Bank Sta=9869.556,10130.43
Exp/Cntr=0.3,0.1

Type RM Length L Ch R = 1 ,6595.829,109.564700,109.564700,109.564700
XS GIS Cut Line= 5
997731.217207691765497.643584451997835.420501163 765420.82780309
997837.026321565765419.635603093997850.798961727765409.353917868
997939.792746474765340.905573527
#Sta/Elev= 30
9869.543 175.8949874.243175.56579886.666173.73469911.513172.68569923.937171.7493
 9936.36171.0703 9941.41170.83979948.784170.64569961.207170.05989973.631168.9913
9975.116168.64649986.054163.90879991.969161.80689998.478161.0032   10001161.1152
10008.75161.690110010.95162.148210018.19164.735110023.49167.136310025.33167.8858
 10036.1170.485410041.73170.938910048.72171.190210061.33170.899310073.95170.9328
10086.57171.239510099.18171.4347 10111.8172.049910123.74173.044410130.46 173.414
#Mann= 3 , 0 , 0
9869.543  0.0686       09869.543  0.0686       010130.46  0.0686       0
#XS Ineff= 2 , 0
       0                               0
Bank Sta=9869.543,10130.46
Exp/Cntr=0.3,0.1

Type RM Length L Ch R = 1 ,6486.264,62.161700,62.161700,62.161700
XS GIS Cut Line= 2
997819.731776774 765583.70826076998004.627610147765413.135344103
#Sta/Elev= 25
9883.191163.92329890.358163.56129896.033163.54369910.781163.21639917.569163.1561
9931.174163.28789940.277163.5998 9944.78163.28829955.025161.84619969.773160.8049
9984.521158.87529985.596158.80639999.268158.423210012.81158.277910026.41158.4901
10043.51157.964810058.26158.162810067.23157.944810073.01158.616310080.83159.1903
10094.44164.8569 10102.5166.362210108.04167.9124   10132170.039410134.75170.2161
#Mann= 3 , 0 , 0
9883.191    0.06       09883.191    0.06       010134.75    0.06       0
#XS Ineff= 2 , 0
       0                10022.71       0
Bank Sta=9883.191,10134.75
Exp/Cntr=0.3,0.1

Type RM Length L Ch R = 1 ,6424.103,152.273600,152.273600,152.273600
XS GIS Cut Line= 3
 997830.14844349 765607.14576076 997916.08594346765574.593677431
 998033.27344352 765474.33326076
#Sta/Elev= 24
9854.616161.64669860.673161.1889 9881.19160.40429891.884160.38399902.577 160.033
9913.271160.05069917.134160.27189923.964160.86779934.657 160.3649945.351160.4424
9958.243159.15539961.269158.31199971.404155.86929984.564155.45719992.034155.3666
10007.42155.359510010.88155.5501 10022.8158.044710024.05158.398810037.21160.9325
10068.95164.451710076.69164.925710089.85165.199110100.74165.5396
#Mann= 3 , 0 , 0
9854.616    0.06       09854.616    0.06       010100.74    0.06       0
#XS Ineff= 2 , 0
       0                               0
Bank Sta=9854.616,10100.74
Exp/Cntr=0.3,0.1

Type RM Length L Ch R = 1 ,6271.829,188.669900,188.669900,188.669900
XS GIS Cut Line= 6
997941.281534884765731.889503807997978.801208822765711.755118004
998010.513466226765691.149330617998032.202133749765673.095284045
998076.232316468765628.238365654998149.417855788765577.122541381
#Sta/Elev= 30
9869.592 149.7989885.161150.3626 9896.51150.62419905.311150.93899919.566151.5884
9931.491151.8813 9955.83 151.8619959.604151.78019968.841151.15419975.234149.9877
9978.212148.9444 9982.32147.24279989.266 144.9139997.005144.542210002.84144.9547
10011.87147.392110016.39149.251110018.18149.792910025.94151.937310031.08 152.789
10039.46153.700310052.11154.836910063.12156.064310064.63156.401710076.72  158.33
   10080  158.5610089.14158.763310113.13161.305910116.18161.659410130.43163.8029
#Mann= 3 , 0 , 0
9869.592    0.12       09869.592    0.12       010130.43    0.12       0
#XS Ineff= 2 , 0
       0                               0
Bank Sta=9869.592,10130.43
Exp/Cntr=0.3,0.1

Type RM Length L Ch R = 1 ,6083.159,188.669900,188.669900,188.669900
XS GIS Cut Line= 6
997972.619799705765829.401581445998014.989760535765825.213460271
998052.809816662765824.783100669998123.962153732765833.954734423
998157.050493008765835.224872736998232.007028047765826.725465885
#Sta/Elev= 26
 9869.58144.02519871.972144.59729882.021145.03339892.069145.34819902.118145.5298
9912.167145.50559922.167145.02539952.176145.26939962.207144.41339972.238143.2637
9982.294139.3744 9992.44135.8536 10002.6135.222710012.72135.731810022.82142.7461
10032.83146.661810042.84147.877310052.85148.968710062.86149.939410072.88150.3033
 10082.9149.996610092.97150.516610103.09150.2286 10113.2150.122110123.32149.4439
10130.41149.2597
#Mann= 3 , 0 , 0
 9869.58    0.12       0 9869.58    0.12       010130.41    0.12       0
#XS Ineff= 2 , 0
       09932.299                       0
Bank Sta=9869.58,10130.41
Exp/Cntr=0.3,0.1

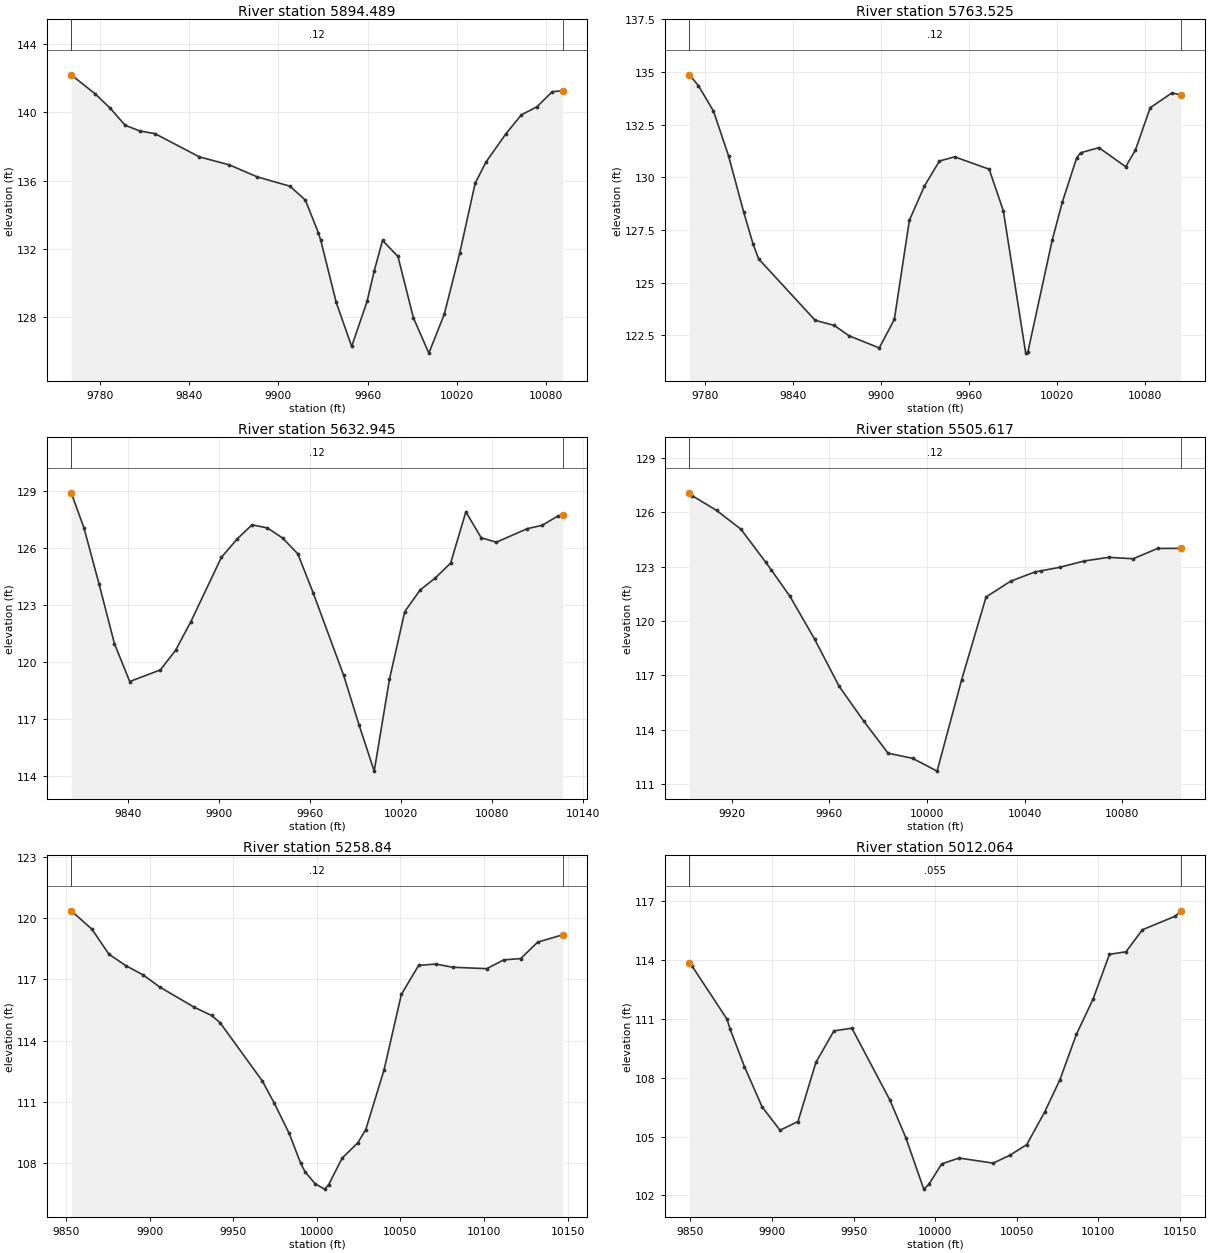
Type RM Length L Ch R = 1 ,5894.489,130.964300,130.964300,130.964300
XS GIS Cut Line= 3
997858.794276804 766044.64576076997983.794276804766045.947844103
 998181.71094349765991.260344103
#Sta/Elev= 30
9760.747142.20289776.954141.07789786.955140.24459796.955139.24769806.956138.9062
9816.956138.75629846.958137.38979866.959136.92299885.754136.22099907.755135.6717
9918.129134.8584 9926.86132.94439928.504132.49299938.879128.85759949.253126.2736
9959.628128.91629964.406130.69959970.003132.49069980.378131.55069990.752127.9563
10001.13125.8813 10011.5128.155110021.88131.740310032.25135.8356 10039.5137.0807
   10053138.751710063.38139.859210073.75140.325110084.12141.211510091.09141.2704
#Mann= 3 , 0 , 0
9760.747    0.12       09760.747    0.12       010091.09    0.12       0
#XS Ineff= 2 , 0
       09975.578                       0
Bank Sta=9760.747,10091.09
Exp/Cntr=0.3,0.1

Type RM Length L Ch R = 1 ,5763.525,130.579800,130.579800,130.579800
XS GIS Cut Line= 3
 997959.05469349 766185.27076076998141.346360147766140.999927446
 998259.83594349 766052.45826076
#Sta/Elev= 30
9769.121134.85969775.239 134.3499785.529133.1393 9795.82131.01769806.111128.3594
9812.641126.81439816.401126.12019855.015123.20439867.855  122.979878.146122.4702
9898.727121.89639909.018123.24919919.308 127.9619929.599129.58499939.761130.7664
 9950.18130.96679973.756  130.38 9983.44128.40489998.723121.649410000.15121.6908
10016.85 127.02710023.69128.811110033.56130.931310036.17 131.15810048.66131.4035
10066.97130.499110073.62 131.28810083.68133.296210098.59134.003510104.63133.9031
#Mann= 3 , 0 , 0
9769.121    0.12       09769.121    0.12       010104.63    0.12       0
#XS Ineff= 2 , 0
       09955.738                       0
Bank Sta=9769.121,10104.63
Exp/Cntr=0.3,0.1

Type RM Length L Ch R = 1 ,5632.945,127.328200,127.328200,127.328200
XS GIS Cut Line= 2
 998056.71094346766238.656177446998378.325526804766198.291594088
#Sta/Elev= 30
9802.279128.89179810.633127.05779820.712124.0733 9830.79120.95989840.869 118.972
9861.026119.58099871.104120.61439881.183122.1192 9901.34 125.5029911.942126.4828
9921.496127.20899931.575127.05029941.653126.51899951.732 125.684 9961.81123.6462
9981.967 119.2989992.244116.661610002.12114.2609 10012.2119.099910022.28122.6503
10032.36123.777210042.44124.420110052.52125.194510062.59127.893910072.67126.5304
10082.75126.296510102.91127.003810112.99127.185810123.07127.664110126.42127.7336
#Mann= 3 , 0 , 0
9802.279    0.12       09802.279    0.12       010126.42    0.12       0
#XS Ineff= 2 , 0
       09928.438                       0
Bank Sta=9802.279,10126.42
Exp/Cntr=0.3,0.1

Type RM Length L Ch R = 1 ,5505.617,246.776700,246.776700,246.776700
XS GIS Cut Line= 2
998143.950526804766348.031177446998344.471360147766329.802010775
#Sta/Elev= 24
9902.652 127.0799903.705126.92689913.747126.11269923.788125.06469933.829123.2636
9936.132 122.835 9943.87121.35719953.912119.01159963.953116.40659973.994114.4916
9984.035112.70459994.076112.422810004.12 111.71510014.16116.7461 10024.2 121.331
10034.24122.200210044.28122.712910046.59122.769510054.32122.966210064.37123.3152
10074.41 123.51810084.45123.440310094.49124.0076   10104124.0161
#Mann= 3 , 0 , 0
9902.652    0.12       09902.652    0.12       0   10104    0.12       0
#XS Ineff= 2 , 0
       0 9949.49                       0
Bank Sta=9902.652,10104
Exp/Cntr=0.3,0.1

Type RM Length L Ch R = 1 , 5258.84,246.776600,246.776600,246.776600
XS GIS Cut Line= 6
998142.763736421766556.878489263998256.375051833766577.087054683
998270.073357135766571.761768244998292.435952632766549.369993996
 998311.45742191766539.371490159998419.726418265766517.759502836
#Sta/Elev= 30
9853.091120.34899865.507 119.4499875.653118.2271  9885.8117.66769896.016 117.219
9906.287116.61129926.828115.62839937.099115.23179942.112114.88119967.361112.0354
9974.498110.95439983.435109.47419990.346108.00729993.078107.5779    9999107.0053
10004.62106.7423 10007.1 106.96310015.09108.253510024.49109.006110029.29109.6535
10040.24112.579310050.57116.261710060.89117.6795 10071.2117.746710081.35  117.59
10101.65117.5209 10111.8117.950310121.96118.015110132.11118.816710147.06119.1775
#Mann= 3 , 0 , 0
9853.091    0.12       09853.091    0.12       010147.06    0.12       0
#XS Ineff= 2 , 0
       0                               0
Bank Sta=9853.091,10147.06
Exp/Cntr=0.3,0.1

Type RM Length L Ch R = 1 ,5012.064,246.776700,246.776700,246.776700
XS GIS Cut Line= 6
998143.629300725766784.188959675998184.576430498766767.975200265
998283.307076298766722.441954142998303.221572901766714.941367937
998343.667795208766705.299181827998428.280781363 766692.80222766
#Sta/Elev= 29
9849.405113.83339850.879113.7143 9872.39110.99489874.364110.47129883.145108.5647
9893.912106.51769904.923105.32249915.933105.76729926.944108.78899937.955110.3907
9948.966110.52529972.228106.86679981.999104.9475 9993.01102.3175 9996.12102.5593
10003.98103.607310014.66103.903410035.56103.644110045.84104.049110056.12104.5894
10067.08106.246510076.48107.905610086.59110.2234 10096.7112.000110106.81114.2952
10116.92114.425710127.03115.550710147.24116.245310150.56116.5147
#Mann= 3 , 0 , 0
9849.405   0.055       09849.405   0.055       010150.56   0.055       0
#XS Ineff= 2 , 0
       09936.223                       0
Bank Sta=9849.405,10150.56
Exp/Cntr=0.3,0.1

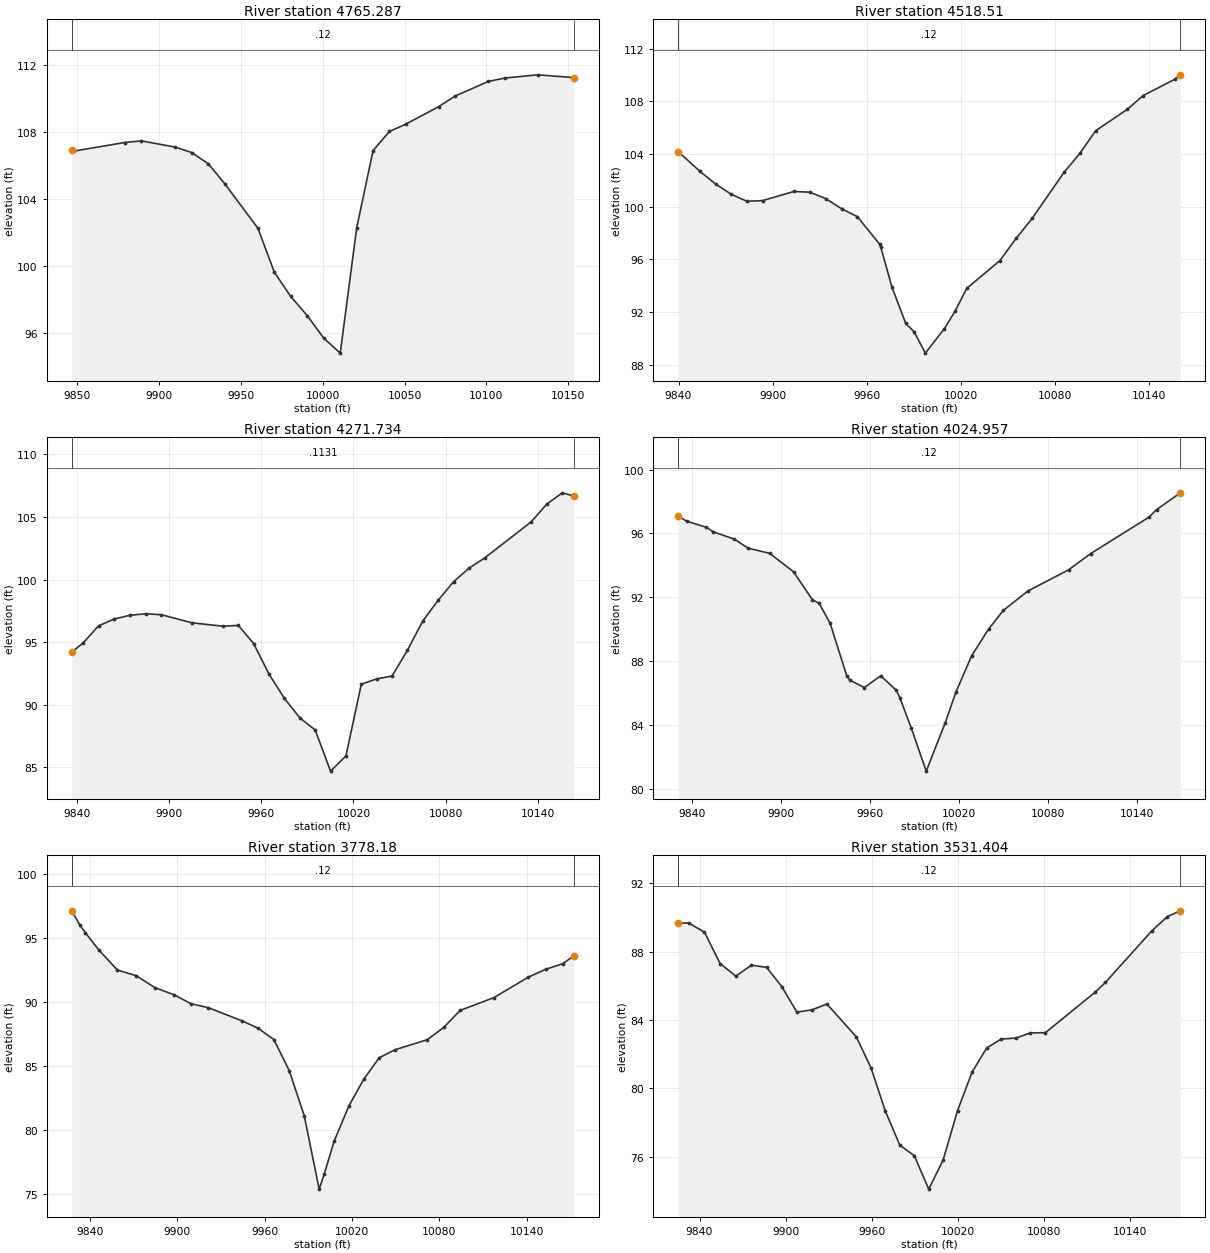
Type RM Length L Ch R = 1 ,4765.287,246.776700,246.776700,246.776700
XS GIS Cut Line= 6
998223.479147096766958.381323812998333.144448634766936.367788073
998354.736375175766935.686709631998390.719909769766940.629540349
998418.570839365766940.783046701998526.799504917766927.128222568
#Sta/Elev= 24
 9846.61 106.9149848.168106.84029878.904107.3494 9889.15107.44699909.641107.0804
9919.886 106.7539930.014106.08339940.139104.88529960.368102.23269970.37399.62035
 9980.3898.167689990.46997.0271310000.5795.6799210010.66 94.784210020.72 102.257
10030.72106.868310040.72108.009810050.74108.445610070.83109.491210080.87 110.122
10101.07110.989710111.17111.194210131.38111.387410153.41111.2201
#Mann= 3 , 0 , 0
 9846.61    0.12       0 9846.61    0.12       010153.41    0.12       0
#XS Ineff= 2 , 0
       0                               0
Bank Sta=9846.61,10153.41
Exp/Cntr=0.3,0.1

Type RM Length L Ch R = 1 , 4518.51,246.776700,246.776700,246.776700
XS GIS Cut Line= 6
998221.217767476767199.262796613998335.923113381767189.665456433
998356.927588693767179.639705574 998379.84192459767149.382961511
998397.693799758767138.952675904998518.640350176767118.940342521
#Sta/Elev= 30
 9839.83104.18379853.624102.69059863.632101.7269 9873.64 100.9479883.648100.4122
9893.656100.46389913.708101.16299923.824101.0977 9933.94100.61539944.05799.84531
9954.17399.24163 9968.3597.152769968.99696.953249976.21693.885689984.93691.14916
 9990.3690.492529997.50288.8787410009.6790.7424210016.5792.0824510023.88 93.7955
10044.9795.8952410055.3997.5898510065.6499.1102410086.03102.6158 10096.1104.0487
10106.17105.774710126.31107.392310136.38108.434310156.53109.674310160.19110.0194
#Mann= 3 , 0 , 0
 9839.83    0.12       0 9839.83    0.12       010160.19    0.12       0
#XS Ineff= 2 , 0
       0                               0
Bank Sta=9839.83,10160.19
Exp/Cntr=0.3,0.1

Type RM Length L Ch R = 1 ,4271.734,246.776600,246.776600,246.776600
XS GIS Cut Line= 6
 998248.03300409767353.733222431998293.763227823 767364.30472374
998330.091440131767369.079548621998372.172410784767370.876581471
998465.133543226767368.566250343998572.418343074767383.215306925
#Sta/Elev= 30
9836.47594.217559843.62694.900969853.889  96.2999864.15396.846269874.41797.14854
9884.65997.265869894.74597.191539914.91796.540949934.97496.270929944.98396.33791
9954.99294.879679965.00392.43138 9975.0290.505029985.03688.950729995.05287.97169
10005.0784.6893410015.0885.9056310025.0991.6370910035.0992.0614610045.0992.28841
10055.0994.3357810065.1496.6901210075.19  98.35110085.2599.83536 10095.3100.9093
10105.38 101.71910135.77104.6136 10145.9106.029910156.04106.931810163.55106.6797
#Mann= 3 , 0 , 0
9836.475  0.1131       09836.475  0.1131       010163.55  0.1131       0
#XS Ineff= 2 , 0
       0                               0
Bank Sta=9836.475,10163.55
Exp/Cntr=0.3,0.1

Type RM Length L Ch R = 1 ,4024.957,246.776700,246.776700,246.776700
XS GIS Cut Line= 6
998180.613332429767409.570807872998225.766693252767452.939227247
998256.228356026767496.421361507998270.995060148767568.567539255
998281.416327626767588.894401186998370.472918777767675.856597423
#Sta/Elev= 30
9830.85497.082279836.65396.765619849.87196.384029854.44796.106369868.72595.64018
9877.94495.075949892.42294.755879908.55493.598419921.29691.836549925.76291.62778
9933.14790.388689944.39487.082219946.68386.796449956.26986.342039967.33187.08181
9977.82986.16507 9980.16 85.71679987.94483.79114 9997.9581.1064110010.6484.10553
10018.0586.0775610028.5488.3303510040.0290.01664 10049.991.1739510066.4692.39423
10093.8493.7184210108.7894.7389610148.1697.0277110153.1397.4897510169.1798.54549
#Mann= 3 , 0 , 0
9830.854    0.12       09830.854    0.12       010169.17    0.12       0
#XS Ineff= 2 , 0
       0                               0
Bank Sta=9830.854,10169.17
Exp/Cntr=0.3,0.1

Type RM Length L Ch R = 1 , 3778.18,246.776700,246.776700,246.776700
XS GIS Cut Line= 6
 998029.11817575767520.666578629998072.672328466767574.361880312
998096.868680637767611.732718875998108.462920183767640.225611761
998128.305623766767718.271141655998188.644508074767821.446547967
#Sta/Elev= 30
9827.64697.133629833.22696.018729836.98395.417439846.10294.092999858.97892.50631
9871.85492.07059 9884.7391.129949897.545 90.59469909.458 89.87649921.37189.57036
9944.83288.524269955.62887.958919966.42587.076379976.97384.647319987.25281.13745
 9997.5375.39096   1000176.5676810007.8279.1401610017.9781.9046110028.11 83.9711
 10038.785.6479710049.3286.2711710071.7187.0637510083.0288.0220510094.33 89.3538
10117.5390.3540110141.1591.9550910152.9792.5599410164.7893.0073210172.3993.61326
#Mann= 3 , 0 , 0
9827.646    0.12       09827.646    0.12       010172.39    0.12       0
#XS Ineff= 2 , 0
       0                               0
Bank Sta=9827.646,10172.39
Exp/Cntr=0.3,0.1

Type RM Length L Ch R = 1 ,3531.404,158.425600,158.425600,158.425600
XS GIS Cut Line= 6
997865.164719184767608.368675745 997899.91364139767696.566252854
997908.851050755 767737.71402727997921.473823485767840.927989566
 997935.00968553767888.463463223 997957.13818933767943.345152366
#Sta/Elev= 30
9825.16889.684389832.43889.681419843.40389.151289854.36787.306769865.33286.57625
9876.13787.218729886.70587.086929897.27485.961779907.84284.466949918.41184.60665
9928.69784.942579949.16383.027089959.39681.213719969.49678.651969979.54676.67702
9989.59676.063529999.64474.1062410009.6875.8174410019.7178.7048510029.7680.94877
10039.9282.3612810050.0782.8931610060.2282.9481710070.4783.2516510080.8783.26424
10115.6385.6422510122.7186.2098310155.0689.2329210165.8490.0614510174.8490.39799
#Mann= 3 , 0 , 0
9825.168    0.12       09825.168    0.12       010174.84    0.12       0
#XS Ineff= 2 , 0
       0                               0
Bank Sta=9825.168,10174.84
Exp/Cntr=0.3,0.1

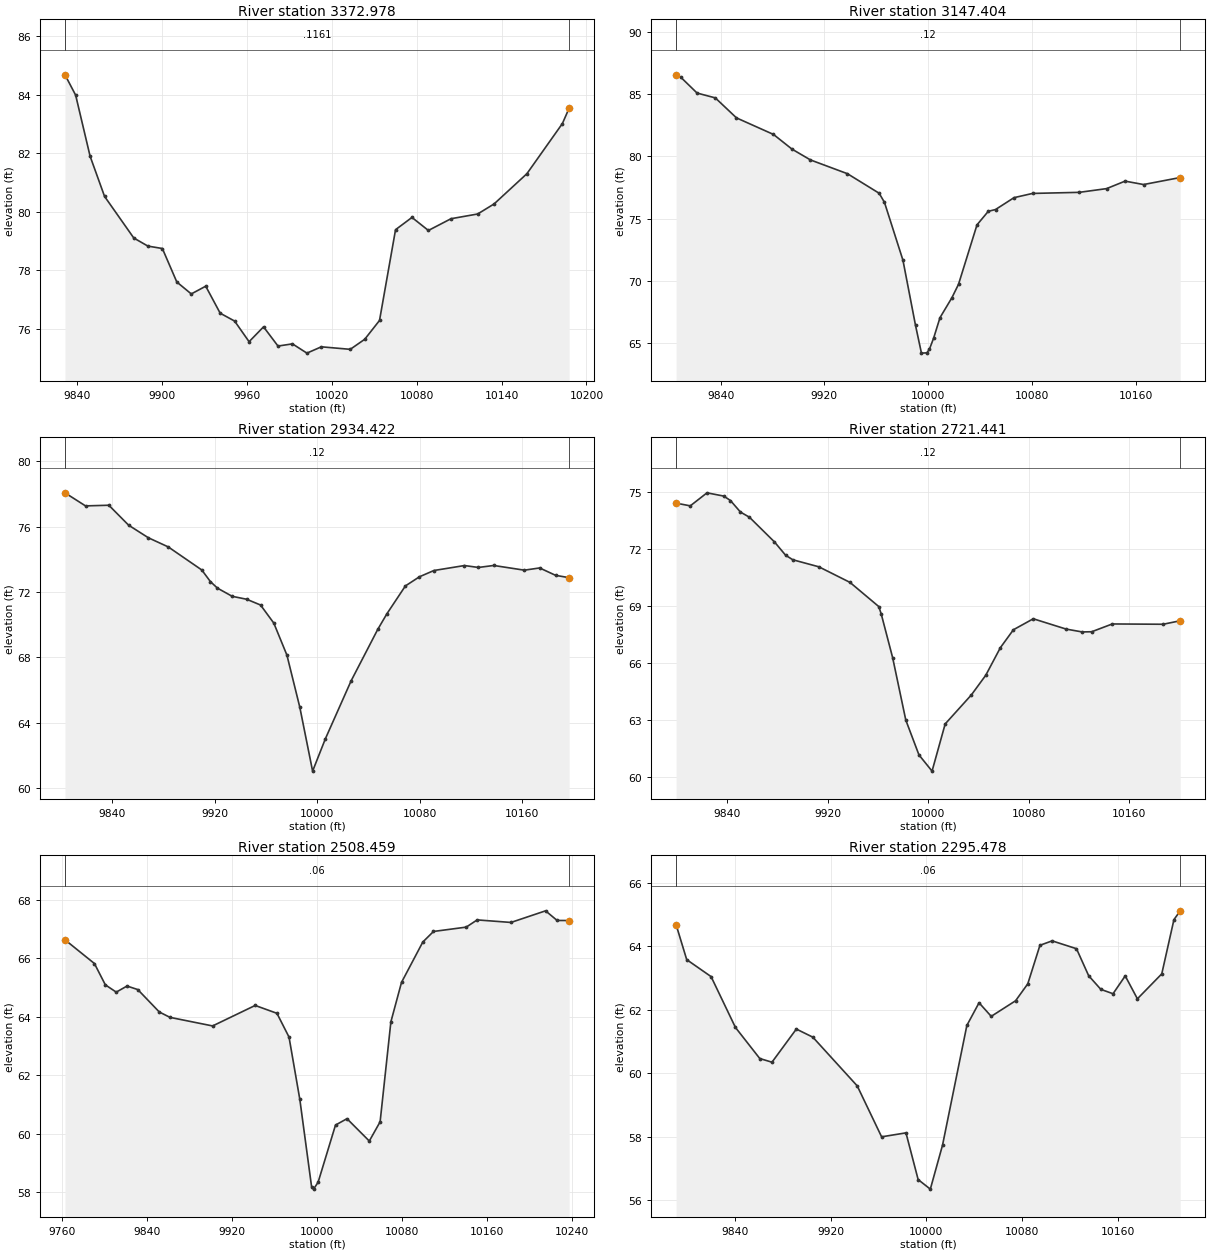
Type RM Length L Ch R = 1 ,3372.978,225.574400,225.574400,225.574400
XS GIS Cut Line= 3
 997794.99219346767647.634633884997749.310769856 767865.24432452
997817.417619586767980.693740577
#Sta/Elev= 30
9831.39284.679299838.91883.985429849.13681.899089859.35480.527089880.02979.10574
9890.00878.829399900.22678.747459910.44477.603179920.66277.19597 9930.8877.45982
9941.09776.537919951.31576.268439961.53375.564139971.75176.071429981.96975.41567
9992.18775.4902710002.4175.1740310012.6275.3895810033.0675.3037510043.28  75.647
10053.7476.2898710065.0779.3896110076.6879.8086610088.2979.36371 10104.379.76505
10123.1279.9259410134.7380.2696110157.9581.3032610183.0383.0158710187.7983.54183
#Mann= 3 , 0 , 0
9831.392  0.1161       09831.392  0.1161       010187.79  0.1161       0
#XS Ineff= 2 , 0
       0                               0
Bank Sta=9831.392,10187.79
Exp/Cntr=0.3,0.1

Type RM Length L Ch R = 1 ,3147.404,212.981500,212.981500,212.981500
XS GIS Cut Line= 4
 997462.32458309767813.447823174997597.921001829767951.211545922
 997599.30195332767952.658257013997734.789512124768090.515852408
#Sta/Elev= 30
9805.69986.543059809.513 86.33239821.90885.07889 9835.9484.69264 9852.2883.08634
9880.79181.758449895.04780.581069909.30279.711979937.81478.606079962.22277.03958
9966.32576.30993 9980.5871.663039990.28466.426479994.83664.20659    999964.22864
   1000164.5241910004.2865.4263710009.13 67.0523 10018.368.65075 10023.469.72787
10037.6674.5024910046.3575.5886310051.9375.7309310066.1976.6843810080.4677.02388
10116.4577.1110210137.5377.4093310151.7978.0111210166.0677.7380510194.2978.30042
#Mann= 3 , 0 , 0
9805.699    0.12       09805.699    0.12       010194.29    0.12       0
#XS Ineff= 2 , 0
       0                               0
Bank Sta=9805.699,10194.29
Exp/Cntr=0.3,0.1

Type RM Length L Ch R = 1 ,2934.422,212.981500,212.981500,212.981500
XS GIS Cut Line= 6
997302.778419247768012.853528346997410.611605314768097.166424688
997440.178478657768107.477076565 997492.37168779768110.172685568
997521.933135639768118.503015671997644.262230024768190.814153513
#Sta/Elev= 30
9802.99778.062549819.01677.263989837.25377.303949852.72276.08499 9868.1975.31354
9883.65874.75814 9909.8873.347539916.594 72.64069922.10372.238349933.66671.73738
 9944.9471.558949955.79471.206329966.17170.098939976.398 68.14489986.46564.96185
9996.47261.0552910006.4863.0381910026.5966.5775810047.3769.7168710054.57 70.6767
10068.9772.3721210079.9872.9334110091.2873.3158310115.1373.6186710126.0373.50186
10137.9973.6231310161.9273.3358510173.8873.4718910186.3373.0204610196.9272.87691
#Mann= 3 , 0 , 0
9802.997    0.12       09802.997    0.12       010196.92    0.12       0
#XS Ineff= 2 , 0
       0                               0
Bank Sta=9802.997,10196.92
Exp/Cntr=0.3,0.1

Type RM Length L Ch R = 1 ,2721.441,212.981500,212.981500,212.981500
XS GIS Cut Line= 6
997216.494752323768066.385388119997309.603359965768159.420869038
997347.304323875768254.969865303 997367.89716375768287.104209745
997409.186316224768323.837337693997470.967051983768362.188610363
#Sta/Elev= 30
9799.15774.419069810.48574.275169823.80474.960949837.12374.790059842.47874.55627
9850.44273.950089857.61773.676269877.551 72.37779886.42371.677369892.161 71.4387
9912.92471.067939937.72170.247869960.64468.976719962.61468.583479971.698 66.2863
9982.17663.003069992.65261.1716510003.0960.3168210013.5562.8000410034.4464.32955
10045.8865.3617410057.5366.8135110067.9167.7564410083.7568.3336910109.9167.79122
10122.7167.6408810130.2867.6511110146.6968.0608610187.1668.0451210200.79 68.2289
#Mann= 3 , 0 , 0
9799.157    0.12       09799.157    0.12       010200.79    0.12       0
#XS Ineff= 2 , 0
       0                               0
Bank Sta=9799.157,10200.79
Exp/Cntr=0.3,0.1

Type RM Length L Ch R = 1 ,2508.459,212.981500,212.981500,212.981500
XS GIS Cut Line= 6
997067.960892543768403.040251756997230.874238774768424.572275824
997337.459109174768386.618194063997383.239142067768380.708574222
997448.787505957768393.535357844997525.386560285768424.703733547
#Sta/Elev= 30
9762.47366.628819790.22165.817119800.48465.088879810.74664.839329820.91965.04768
9831.06164.926959851.34564.159499861.413 63.97599901.55163.682659941.67464.38379
9962.18464.114799973.56363.30154 9983.7361.172119994.81858.182719996.715 58.0995
   1000158.3380810017.3660.2910310028.1860.50922 10049.259.74486 10059.460.40274
10069.5563.8247310079.5665.1727510099.6366.5535710109.6966.9148710140.5267.06341
10150.8667.31057 10182.767.22345 10215.367.6210210226.1967.2913510237.5167.28903
#Mann= 3 , 0 , 0
9762.473    0.06       09762.473    0.06       010237.51    0.06       0
#XS Ineff= 2 , 0
       0                               0
Bank Sta=9762.473,10237.51
Exp/Cntr=0.3,0.1

Type RM Length L Ch R = 1 ,2295.478,172.631500,172.631500,172.631500
XS GIS Cut Line= 2
997066.260220855768563.711417347997480.149109721768642.183639571
#Sta/Elev= 30
9790.79264.689569799.68863.585139820.04463.05108  9840.461.450039860.75760.47011
9870.93560.355149891.29161.398849905.07661.143569942.18259.608139962.53858.00453
9982.895 58.12929993.073 56.657810003.2556.3571410013.4357.7397110033.7961.51415
10043.9662.2266310054.1461.79917 10074.562.2902410084.6862.8236910094.8564.03743
10105.0364.1766910125.3963.9291810135.5763.0775210145.7462.6486910155.9262.51162
 10166.163.0731910176.2862.3515410196.6463.1373510206.8164.8449810212.0565.12274
#Mann= 3 , 0 , 0
9790.792    0.06       09790.792    0.06       010212.05    0.06       0
#XS Ineff= 2 , 0
       0 9920.57                       0
Bank Sta=9790.792,10212.05
Exp/Cntr=0.3,0.1

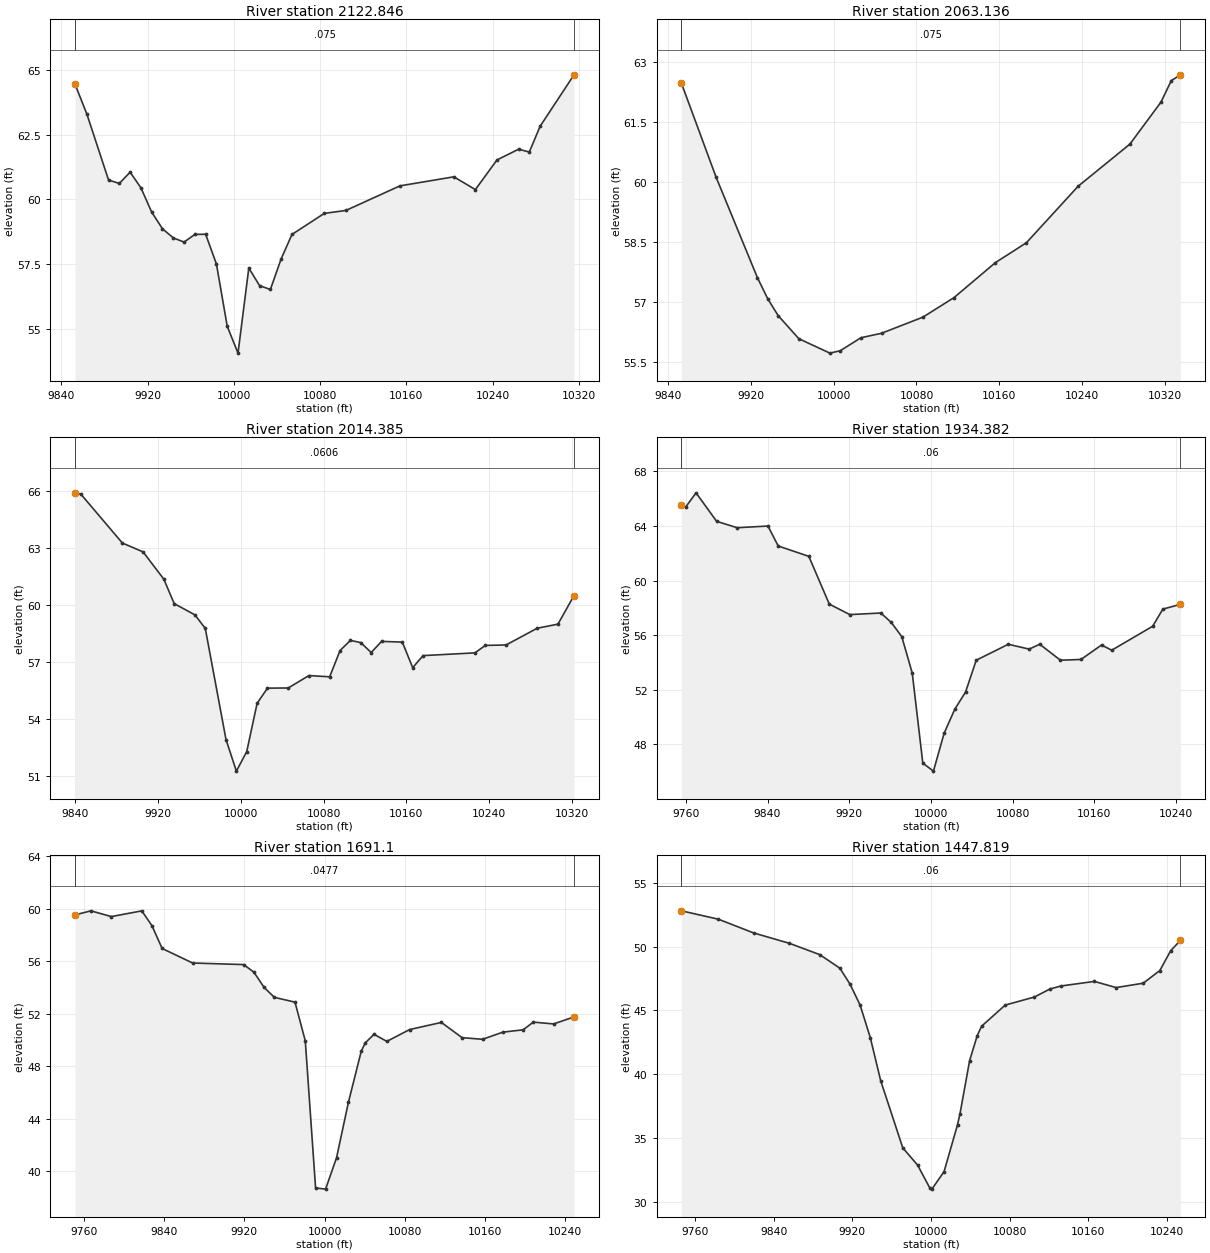
Type RM Length L Ch R = 1 ,2122.846,59.710400,59.710400,59.710400
XS GIS Cut Line= 2
997023.899109691768740.794750676997486.399109751768725.516972899
#Sta/Elev= 30
9852.74164.464699863.84763.291069883.85860.749529893.86460.615889903.86961.05332
9913.87560.44753 9923.8859.505489933.88658.860039943.89158.509289953.89758.34622
9963.90258.642889973.90758.649739983.91357.496279993.91855.0849310003.9254.04734
10013.93 57.341710023.93 56.658610033.9456.5117510043.9557.6983710053.9558.64233
10083.9759.4576910103.9859.5713110154.0160.5220210204.0360.8732910224.0460.37853
10244.0561.5263710264.0761.9402810274.0761.8345610284.0862.8304710315.4964.82172
#Mann= 3 , 0 , 0
9852.741   0.075       09852.741   0.075       010315.49   0.075       0
#XS Ineff= 2 , 0
       0                               0
Bank Sta=9852.741,10315.49
Exp/Cntr=0.3,0.1

Type RM Length L Ch R = 1 ,2063.136,48.750800,48.750800,48.750800
XS GIS Cut Line= 2
997001.507113814768797.151052177997483.880337149768777.928208917
#Sta/Elev= 19
9852.65562.467649886.17560.119939926.20657.605679936.21457.078469946.22256.66096
9966.23856.084069996.26255.7242110006.2755.7838410026.2956.10848 10046.356.22109
10086.3356.6240110116.3657.1123110156.3957.9859210186.4158.4833710236.4559.89592
10286.49 60.947110316.5261.9952410326.5262.5330310335.4162.67872
#Mann= 3 , 0 , 0
9852.655   0.075       09852.655   0.075       010335.41   0.075       0
#XS Ineff= 2 , 0
       0                               0
Bank Sta=9852.655,10335.41
Exp/Cntr=0.3,0.1

Type RM Length L Ch R = 1 ,2014.385,80.003200,80.003200,80.003200
XS GIS Cut Line= 3
996979.280701309768841.003163397997203.346968174768837.999594137
997460.452496886768824.783889398
#Sta/Elev= 30
9840.19165.929489845.91165.855379885.91563.283319905.91662.814489925.91861.37756
9935.91960.089549955.921 59.49649965.92258.781019985.92452.922449995.92451.25911
10005.9352.2892810015.9354.8341510025.9355.6332510045.9355.6423810065.9356.29665
10085.9656.2306910095.9757.6168210105.9958.15015   1011658.0331410126.0157.51163
10136.0358.0973810156.05  58.06210166.0656.7126710176.0857.3485810226.1457.49305
10236.1657.8860510256.1857.9093310286.2258.7916710306.2559.0074310321.7260.51425
#Mann= 3 , 0 , 0
9840.191  0.0606       09840.191  0.0606       010321.72  0.0606       0
#XS Ineff= 2 , 0
       0                               0
Bank Sta=9840.191,10321.72
Exp/Cntr=0.3,0.1

Type RM Length L Ch R = 1 ,1934.382,243.281600,243.281600,243.281600
XS GIS Cut Line= 6
 996920.84628055768922.467476767997009.205872328768931.953000897
997079.891242197768930.864889186997143.496028776768919.199073882
997274.941020716768882.732202265997402.248735213768878.856725993
#Sta/Elev= 30
9755.74765.503489759.93765.391699770.02566.426849790.20164.33676 9810.3263.87048
9840.42263.994039850.43762.532589880.44561.772689900.47358.272999920.54557.50675
9950.91757.622389961.15756.928999971.39755.896169981.655 53.22459992.01546.62469
10002.4246.0390810012.8948.8159310023.37 50.581110033.8451.8326310044.3254.16418
10075.6855.3326910096.1754.9766410106.4255.3362110126.7354.1648610146.8754.22027
10166.9455.2776410176.9554.8969110216.97 56.648910226.9857.9069410244.23 58.2608
#Mann= 3 , 0 , 0
9755.747    0.06       09755.747    0.06       010244.23    0.06       0
#XS Ineff= 2 , 0
       0                               0
Bank Sta=9755.747,10244.23
Exp/Cntr=0.3,0.1

Type RM Length L Ch R = 1 ,  1691.1,243.281600,243.281600,243.281600
XS GIS Cut Line= 6
 996909.31101878769037.701820199997068.729595707769064.972875739
997159.171777024 769085.64788831997206.010536667769119.166728359
997240.002705013769135.282005093997385.060949364769162.779033883
#Sta/Elev= 30
9751.00659.542339766.92359.854419787.21459.415789817.64959.850579827.79558.72279
 9837.9456.984089868.37655.876999919.17755.756879929.44255.182389939.70754.01585
9949.97253.256939970.502 52.89389980.76749.937229991.03238.73341   1000138.64231
10011.9641.0346910023.7745.2510310036.5549.1414210040.6249.7925610049.3250.44271
 10062.149.90289 10084.950.8063210116.5451.3485310137.1750.1869610157.6250.06316
10177.87 50.607810198.1350.7852110208.2651.3724310228.5251.2330810248.84 51.7675
#Mann= 3 , 0 , 0
9751.006  0.0477       09751.006  0.0477       010248.84  0.0477       0
#XS Ineff= 2 , 0
       0                               0
Bank Sta=9751.006,10248.84
Exp/Cntr=0.3,0.1

Type RM Length L Ch R = 1 ,1447.819,243.281600,243.281600,243.281600
XS GIS Cut Line= 6
996958.935133152769224.479571718997164.216018025769278.224354506
997180.808776467769288.749879242997215.754542782769324.170584209
997250.449924469769348.292208189997413.889282124769431.532508374
#Sta/Elev= 30
 9746.2552.816129783.87652.157619819.70351.079919856.15350.266329886.91249.38173
9907.41948.314989917.67247.072359927.92545.43925 9938.4242.848339948.91939.49263
9971.36534.231519986.45732.87497    9999 31.0667   1000130.9899610013.3832.36301
 10027.1  36.04410029.5936.9065510039.3941.06878 10047.143.0240510051.5743.76649
10075.5745.4233310105.3446.0578110121.1146.68682 10132.546.92393 10166.247.27978
10188.4246.7971910215.9447.1390110232.8748.1335810243.9849.6984610253.8650.49878
#Mann= 3 , 0 , 0
 9746.25    0.06       0 9746.25    0.06       010253.86    0.06       0
#XS Ineff= 2 , 0
       0                               0
Bank Sta=9746.25,10253.86
Exp/Cntr=0.3,0.1