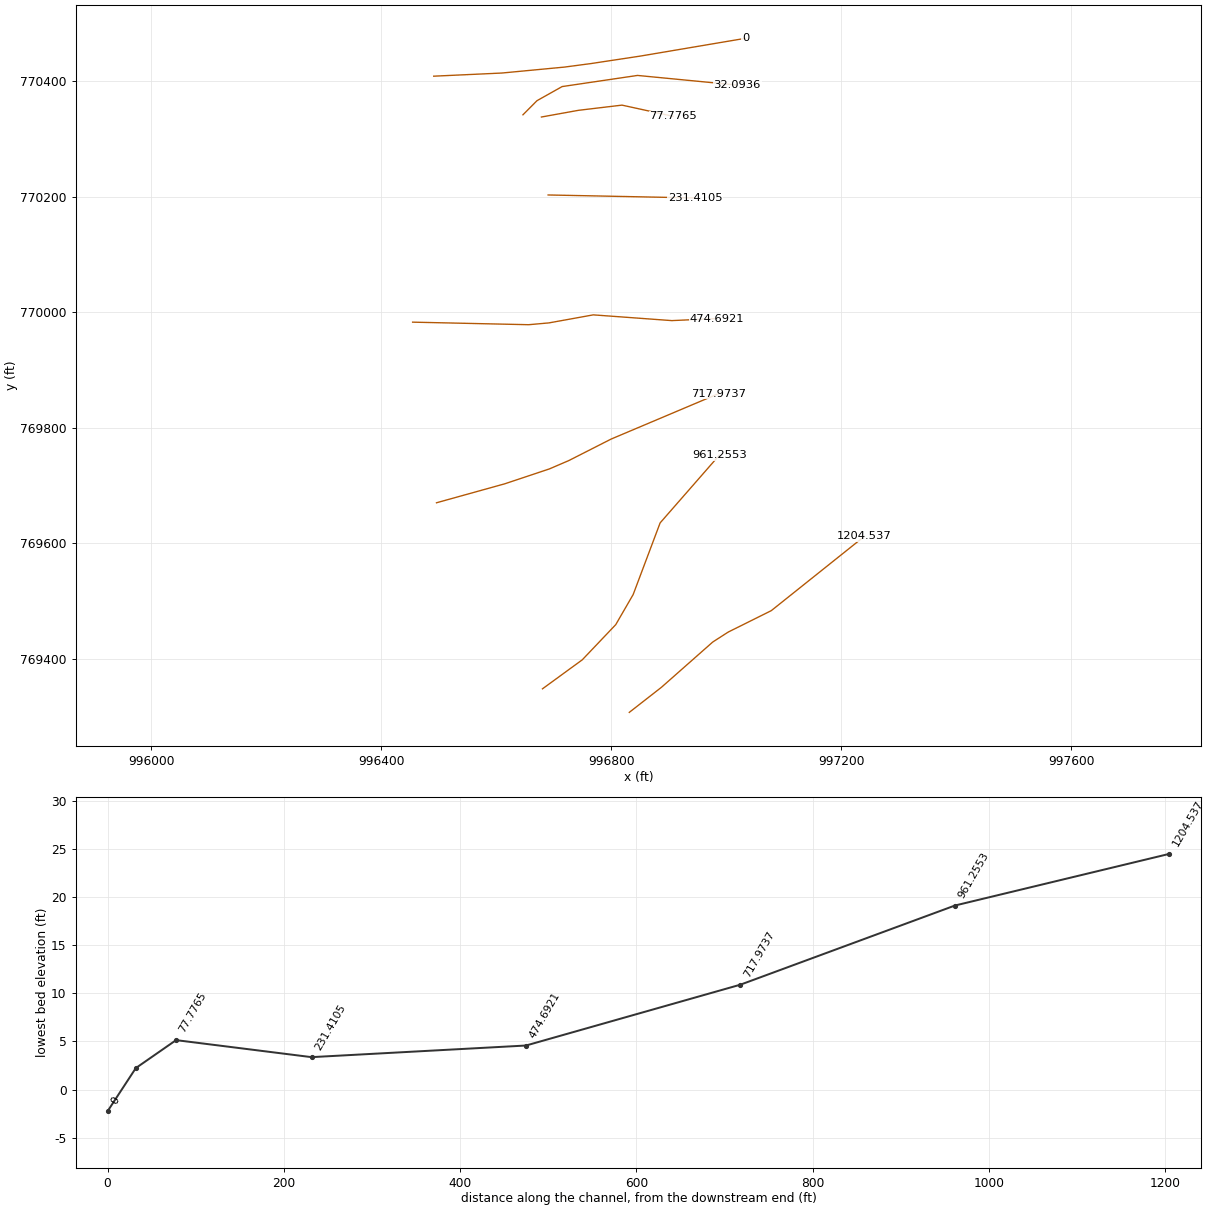
HEC-RAS study 157_ras.prj: 157

--- 157_ras.g01 (geometry) --- (continued)

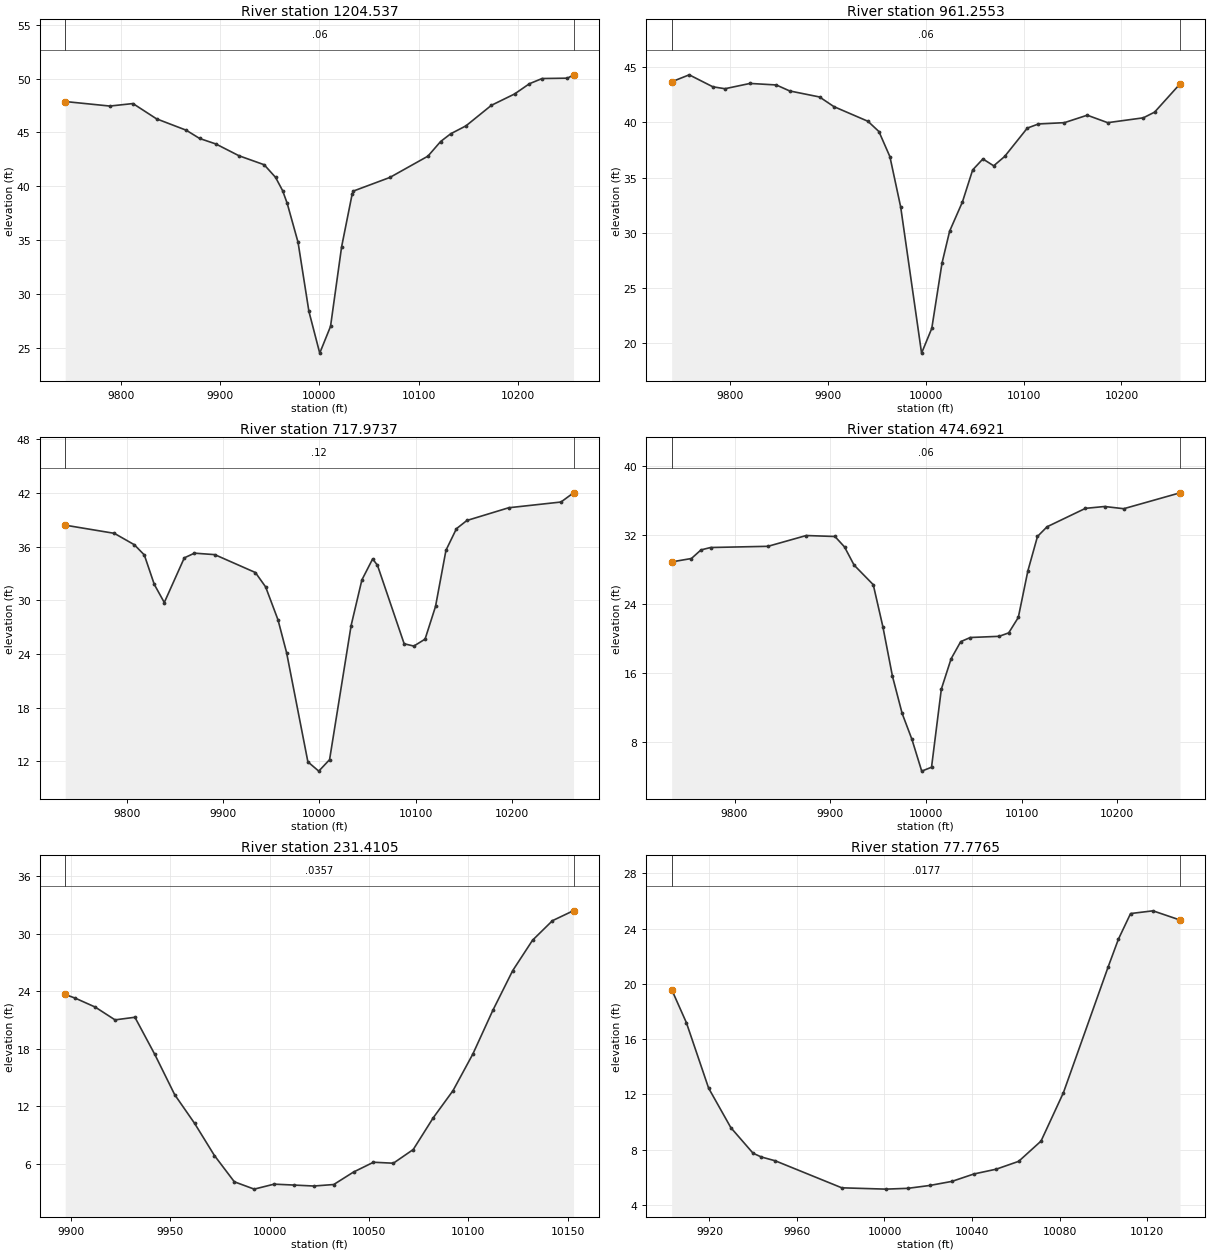
Type RM Length L Ch R = 1 ,1204.537,243.281600,243.281600,243.281600
XS GIS Cut Line= 6
 996831.12776403769307.442069785996887.131542273769350.923433887
996976.346984258769429.257553558997003.090892153769446.366046757
997078.089013647769483.510718749997239.780916844769611.931288463
#Sta/Elev= 30
9744.13147.878959789.067 47.45839812.334 47.69089836.06246.270719865.94245.21253
9879.46344.443559895.82143.931759919.15542.833239944.44242.000459955.92940.82262
9962.99939.592589967.62138.409299978.55234.785139989.48328.3580110000.38 24.4788
10011.2526.9660510022.4234.3771510032.9739.2486110034.1139.54762   1007140.81927
10109.3142.7992410122.0844.1600210132.1944.8784910147.6245.6181110173.1647.52581
10196.5148.5806610211.4849.5361110224.2550.0183610249.7950.0504110255.8950.36299
#Mann= 3 , 0 , 0
9744.131    0.06       09744.131    0.06       010255.89    0.06       0
#XS Ineff= 2 , 0
       0                               0
Bank Sta=9744.131,10255.89
Exp/Cntr=0.3,0.1

Type RM Length L Ch R = 1 ,961.2553,243.281600,243.281600,243.281600
XS GIS Cut Line= 6
996680.162470892 769348.19513711996749.396070646769398.391571103
996807.603748356769459.288609918996837.850819256769511.291892399
996884.736033579769635.303649003996987.721436516769752.551192372
#Sta/Elev= 30
9740.11343.67478 9758.0544.305939782.22843.221939794.59143.047999820.21343.52671
9847.05943.388759860.75842.847829891.30142.301449906.04141.425269940.79440.10098
9952.02539.171199963.25536.897679974.28732.334589995.63119.1144810006.0721.35317
10016.5227.2606610024.3230.1544610037.4232.8032310047.8835.7001410058.3336.69102
10069.3836.0701910080.56 36.914310103.7539.4836810115.0639.8561610141.6939.97655
10165.0440.6518310185.9339.9753210222.3840.4137710233.9140.9302710259.8743.48022
#Mann= 3 , 0 , 0
9740.113    0.06       09740.113    0.06       010259.87    0.06       0
#XS Ineff= 2 , 0
       0                               0
Bank Sta=9740.113,10259.87
Exp/Cntr=0.3,0.1

Type RM Length L Ch R = 1 ,717.9737,243.281600,243.281600,243.281600
XS GIS Cut Line= 6
996495.888934707769670.154328885996614.451839512769702.935850418
996692.205297888769728.755448707996726.230179945769743.312599408
996799.487261749 769780.37195239996987.011203154769859.253358805
#Sta/Elev= 30
9736.25938.386549787.21337.474739807.96336.202249818.339 35.06059828.71431.76289
9839.08929.742359859.84834.733729870.38535.259139891.45935.093449933.607 33.0947
9944.23931.487249957.07427.806539965.99224.13744  9988.111.932989999.38710.89995
 10010.612.1847310032.9527.1731310044.1232.26749 10055.334.6188310060.3133.89775
10087.9925.1334410098.0424.8753410109.6825.6498310120.5329.2999110131.3835.58186
10142.2337.9913110153.0838.9098510196.4740.3327510250.7240.9736110263.7542.00109
#Mann= 3 , 0 , 0
9736.259    0.12       09736.259    0.12       010263.75    0.12       0
#XS Ineff= 2 , 0
       0                               0
Bank Sta=9736.259,10263.75
Exp/Cntr=0.3,0.1

Type RM Length L Ch R = 1 ,474.6921,243.281600,243.281600,243.281600
XS GIS Cut Line= 6
996454.374695883769982.724832912996656.076884611769978.308453914
996691.262502896769981.425322296996768.509467734769995.340164213
996905.094728057769985.401316592   996983.663352769988.961614872
#Sta/Elev= 30
9734.30328.872219754.93329.266979764.93530.263599774.938 30.54329834.95230.68281
9874.96231.935089904.96931.822319914.97130.611779924.97428.502939945.01126.22691
 9955.0521.357699965.08915.59237  9975.211.282689985.4298.2731679995.6584.582227
10005.925.03381710016.1814.1078210026.3917.6270210036.4319.6161310046.4820.09593
10076.5620.2331310086.5920.6325410096.6222.4221210106.64 27.834410116.6731.82791
 10126.732.95124 10166.835.0896210186.8635.3046810206.8635.0485510265.6436.89223
#Mann= 3 , 0 , 0
9734.303    0.06       09734.303    0.06       010265.64    0.06       0
#XS Ineff= 2 , 0
       0                               0
Bank Sta=9734.303,10265.64
Exp/Cntr=0.3,0.1

Type RM Length L Ch R = 1 ,231.4105,153.634000,153.634000,153.634000
XS GIS Cut Line= 2
996689.937377244770202.830731779 996945.61601755770197.691462621
#Sta/Elev= 28
9897.13623.68609  9902.223.303269912.20222.376179922.20421.036779932.20621.31003
9942.208 17.4339 9952.2113.233539962.21210.245089972.214 6.881369982.2164.141574
9992.2183.37537710002.223.89529710012.22 3.7997810022.223.69972610032.233.856826
10042.235.16293910052.23 6.1811710062.23 6.0801210072.237.50835810082.2410.80429
10092.2413.6551310102.2417.4830610112.24  22.01810122.2426.1689610132.2529.34999
10142.2531.3864610152.2532.3736710152.8732.41621
#Mann= 3 , 0 , 0
9897.136  0.0357       09897.136  0.0357       010152.87  0.0357       0
#XS Ineff= 2 , 0
       0                               0
Bank Sta=9897.136,10152.87
Exp/Cntr=0.3,0.1

Type RM Length L Ch R = 1 , 77.7765,45.682900,45.682900,45.682900
XS GIS Cut Line= 4
996678.374021679770337.736547008996742.614886045770349.299902588
996818.419106036770358.293623596 996907.07149893770339.021364287
#Sta/Elev= 22
9902.72819.584219909.46117.185599919.62212.447519929.7829.5889479939.9437.736863
 9943.737.4674099950.1047.1905329980.4745.23722110000.61 5.1419210010.685.199771
10020.755.40792410030.82 5.7027510040.896.23916910051.076.58547710061.317.151976
10071.548.61764910081.7712.1186410102.2421.2309810106.9223.2332310112.4725.08434
10122.7125.2810510135.0624.61572
#Mann= 3 , 0 , 0
9902.728  0.0177       09902.728  0.0177       010135.06  0.0177       0
#XS Ineff= 2 , 0
       0                               0
Bank Sta=9902.728,10135.06
Exp/Cntr=0.3,0.1

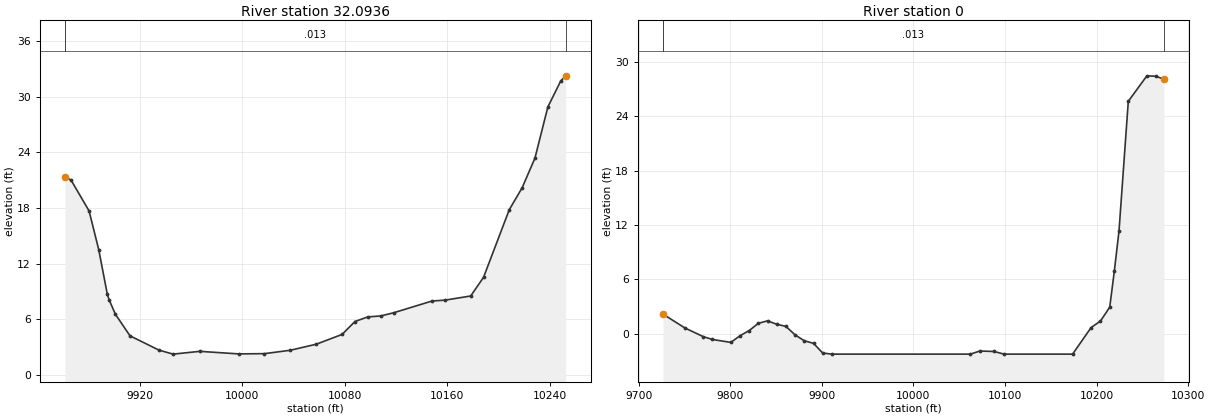
Type RM Length L Ch R = 1 , 32.0936,32.093600,32.093600,32.093600
XS GIS Cut Line= 5
996646.253589451770341.590998858996670.665117919770366.002527326
996714.348905712770390.414055794996845.400269121770409.686315119
997018.850602955770392.983690381
#Sta/Elev= 30
9861.25221.313629866.07321.011099880.21517.667369887.76313.485549894.3578.754473
9895.7758.1182189900.7416.5418229912.1964.2070819934.7182.6765819945.8172.239348
 9966.692.5389799997.0132.26397510017.232.29047110037.442.65744710057.663.305578
10077.874.36427710087.925.75512110097.976.25111210108.016.35218410118.066.694689
 10148.27.96632210158.258.05753510178.348.50664810188.3810.5144910208.4817.80387
10218.5220.1656310228.5723.3784810238.6228.8792510248.6631.6749910252.5332.23788
#Mann= 3 , 0 , 0
9861.252   0.013       09861.252   0.013       010252.53   0.013       0
#XS Ineff= 2 , 0
       0                               0
Bank Sta=9861.252,10252.53
Exp/Cntr=0.3,0.1

Type RM Length L Ch R = 1 ,       0,0.000000,0.000000,0.000000
XS GIS Cut Line= 6
 996491.06067261770408.394601586996609.425033863770413.836550506
996718.248195461770424.109284773 996764.42501237770430.211828451
996850.324558485770443.169183437997033.269660335770473.971239764
#Sta/Elev= 30
9726.6252.158643 9750.590.6308379770.611-0.321939780.622-0.634379800.643-0.95328
9810.653-0.221529820.6640.3486479830.6741.1483379840.6851.4216249850.714 1.04575
9860.7590.8104369870.803-0.127349880.848-0.774159890.892-1.056789900.937-2.12696
9910.981-2.2483610062.26-2.2483610072.37-1.9063510087.87-1.95557 10098.9-2.24836
10173.74-2.2483610194.02  0.687810204.161.395988 10214.32.92818910219.366.931289
10224.44 11.347910234.5825.6330510254.8628.4425810265.0128.3929310273.39 28.0564
#Mann= 3 , 0 , 0
9726.625   0.013       09726.625   0.013       010273.39   0.013       0
#XS Ineff= 2 , 0
       0                               0
Bank Sta=9726.625,10273.39
Exp/Cntr=0.3,0.1